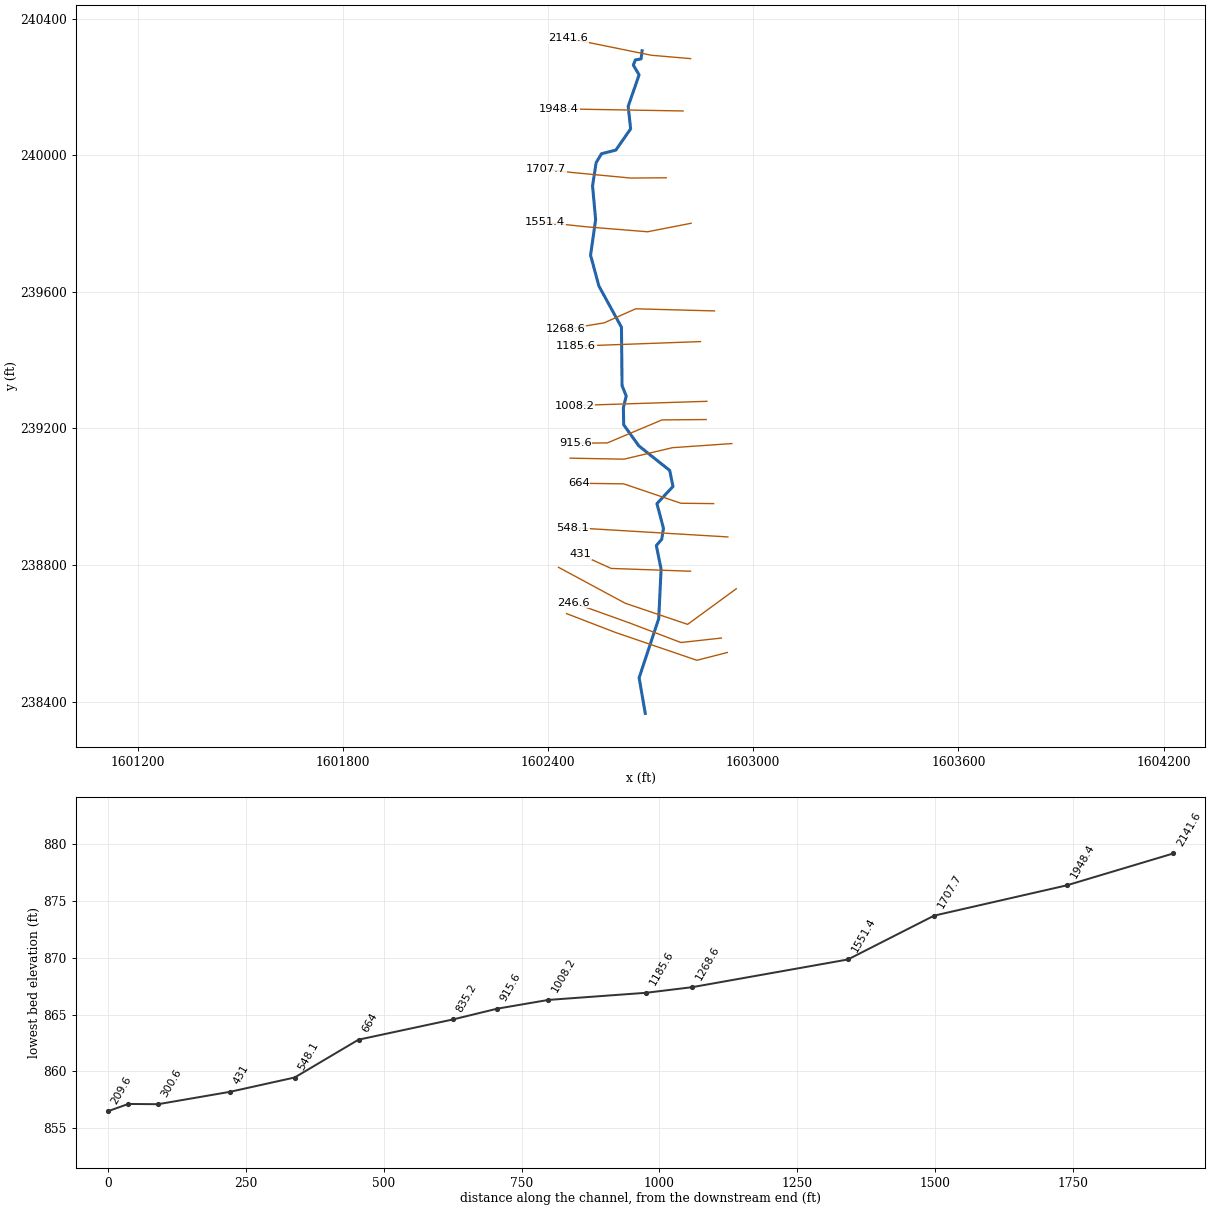
--- MUDLICKRN.prj (project) ---

Proj Title=MUDLICKRN
Current Plan=p01
Default Exp/Contr=0,0
English Units
Geom File=g01
Flow File=f01
Plan File=p01
BEGIN DESCRIPTION:
END DESCRIPTION:
DSS Export Rating Curves= 0
DSS Export Rating Curve Sorted= 0
DSS Export Volume Flow Curves= 0
DXF OffsetX= 0
DXF OffsetY= 0
DXF ScaleX= 0
DXF ScaleY= 0

--- MUDLICKRN.p01 (plan) ---

Plan Title=Floodplain
Program Version=4.00
Geom File=g01
Flow File=f01
K Sum by GR=0
Std Step Tol=0.01
Critical Tol=0.01
Num of Std Step Trials=20
Max Error Tol=0.3
Flow Tol Ratio=0.001
Split Flow NTrial=30
Split Flow Tol=0.02
Split Flow Ratio=0.02
Log Output Level=0
Friction Slope Method=1
Unsteady Friction Slope Method=2
Unsteady Bridges Friction Slope Method=1
Global Log Level=0
CheckData=False
Run HTab=0
Run UNet=0
Run PostProcess=0
UNET Theta=0
UNET Theta Warmup=0
UNET ZTol=0
UNET ZSATol=0
UNET MxIter=0
UNET MaxInSteps=0
UNET DtIC=0
UNET DtMin=0
UNET MaxCRTS=0
UNET WFStab=0
UNET SFStab=0
UNET WFX=0
UNET SFX=0
UNET DSS MLevel=0
UNET DZMax Abort=0
UNET Convert EG Bridges=0
UNET Use Existing IB Tables=0
UNET Froude Limit=0
UNET Froude Power=0
Write IC File=0
Echo Input=False
Echo Output=False
Write Detailed=0

--- MUDLICKRN.f01 (steady flow) ---

Flow Title=NFF Regression Equation
Program Version=4.10
Number of Profiles= 1
Profile Names=P100yr
River Rch & RM=MUDLICKRN,Main            ,2141.6
456.6188
River Rch & RM=MUDLICKRN,Main            ,548.1
 478.905
River Rch & RM=MUDLICKRN,Main            ,431
 481.288
Boundary for River Rch & Prof#=MUDLICKRN,Main            , 1
Up Type= 0
Dn Type= 3
Dn Slope=0.01737
DSS Import GetInterval= 0
DSS Import GetPeak= 0
DSS Import FillOption= 0

--- MUDLICKRN.g01 (geometry) ---

Geom Title=USGS 10m DEM
Program Version=4.10

River Reach=MUDLICKRN       ,Main
Reach XY= 30
       1602675.1      240306.597     1602672.117      240282.733
     1602655.214      240279.608     1602649.532      240264.693
     1602666.271      240235.968     1602634.469      240143.712
     1602641.543      240077.693     1602598.189      240015.369
     1602556.377      240004.916     1602540.697      239978.783
     1602530.244      239910.837      1602539.25      239811.738
     1602524.494      239707.571     1602548.799      239617.294
     1602614.771      239496.634     1602616.508      239325.627
      1602628.66      239295.245     1602620.414      239261.044
     1602621.282      239210.696     1602665.553      239149.064
      1602755.83      239077.016     1602765.379      239030.141
     1602718.504      238979.794     1602737.601      238907.398
     1602732.393       238875.28     1602716.768       238857.05
     1602730.657      238787.606     1602723.712      238643.162
     1602666.421      238469.551     1602684.307        238365.3

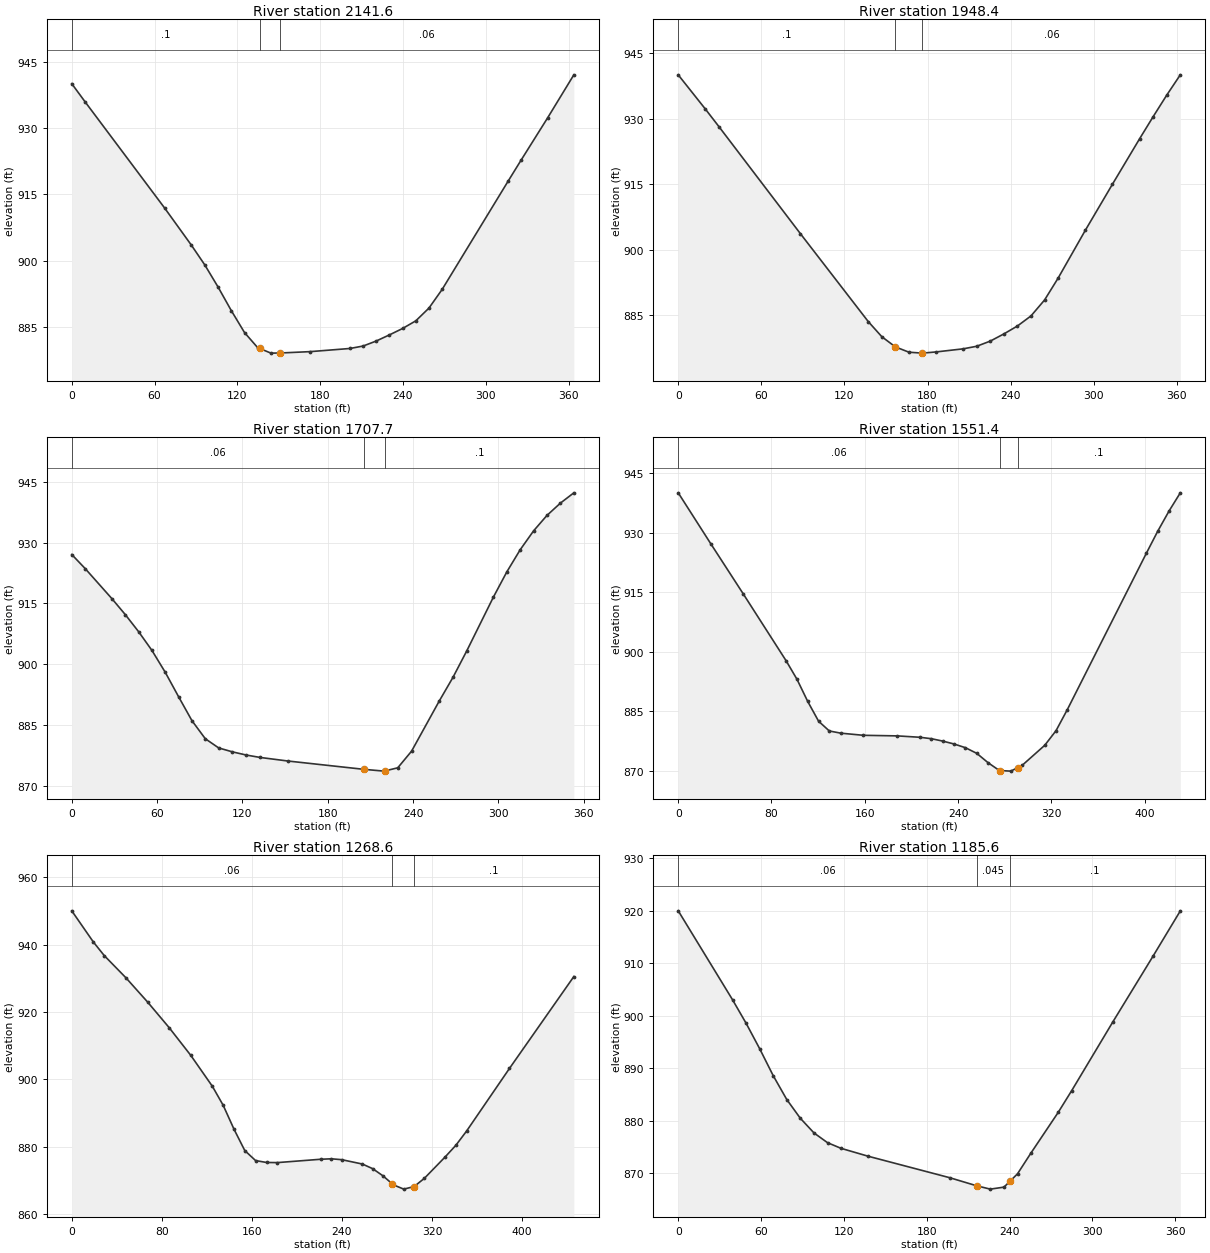
Type RM Length L Ch R = 1 ,2141.6  ,187.4,193.3,192.5
XS GIS Cut Line= 3
     1602816.903      240283.484     1602701.699      240293.491
      1602458.47      240342.971
#Sta/Elev= 25
       0     940     9.6  935.93    67.5  911.85    86.7  903.55    96.4   899.1
     106  894.12   115.6  888.79   125.2  883.83   134.7  880.44   136.2  880.25
   144.3   879.2   151.2  879.23   172.9  879.54   201.6  880.25   211.1   880.8
   220.6  881.93   230.2  883.32   239.7  884.76   249.3  886.49   258.8  889.36
   268.4  893.59   316.1  917.97   325.7  922.81   344.8  932.29   363.8     942
#Mann= 3 , 0 , 0
       0      .1       0   136.2    .045       0   151.2     .06       0
Bank Sta=136.2,151.2
XS Rating Curve= 0 ,0
Exp/Cntr=0.3,0.1

Type RM Length L Ch R = 1 ,1948.4  ,242.8,240.7,238.5
XS GIS Cut Line= 2
     1602794.894      240130.193     1602432.467       240136.43
#Sta/Elev= 24
       0     940    19.6  932.18    29.4  928.16    88.2   903.7   137.2   883.6
     147  880.14   156.8  877.81   166.6   876.6   176.3  876.39   186.1  876.66
   205.7  877.37   215.5  877.96   225.3  879.14   235.1  880.78   244.9  882.59
   254.7   884.9   264.5  888.54   274.3  893.55   293.9  904.46   313.5     915
   333.1  925.39   342.9  930.45   352.7  935.37   362.5  940.01
#Mann= 3 , 0 , 0
       0      .1       0   156.8    .045       0   176.3     .06       0
Bank Sta=156.8,176.3
XS Rating Curve= 0 ,0
Exp/Cntr=0.3,0.1

Type RM Length L Ch R = 1 ,1707.7  ,156,156.3,156.5
XS GIS Cut Line= 4
     1602745.622      239934.464     1602642.324      239933.596
     1602468.713      239950.089      1602394.06      239959.637
#Sta/Elev= 30
       0  927.05     9.4   923.6    28.2  916.19    37.6  912.27      47  908.05
    56.4  903.42    65.7  898.07    75.1  892.04    84.5  886.14    93.9  881.69
   103.3  879.43     113  878.46   122.7  877.68   132.4  877.09   151.7  876.22
   205.4  874.16   219.6  873.72   220.4  873.79   229.2  874.54   238.9  878.63
   258.3  890.94     268   896.8   277.7  903.32   296.5  916.61   305.9  922.79
   315.3  928.24   324.7  932.88   334.1  936.68   343.6  939.72     353  942.24
#Mann= 3 , 0 , 0
       0     .06       0   205.4    .045       0   220.4      .1       0
Bank Sta=205.4,220.4
XS Rating Curve= 0 ,0
Exp/Cntr=0.3,0.1

Type RM Length L Ch R = 1 ,1551.4  ,270.7,282.7,294.3
XS GIS Cut Line= 4
     1602818.342      239801.178     1602691.115       239776.27
     1602516.618      239790.372     1602391.323      239803.563
#Sta/Elev= 30
       0     940    27.8  927.22    55.6  914.61    92.6  897.65   101.9  892.99
   111.1  887.41   120.4  882.44   129.6  879.98   139.4  879.43   158.8  878.89
     188  878.74   207.4  878.39   217.2  878.03   226.9  877.43   236.6   876.7
   246.4  875.76   256.1  874.34   265.8  871.98   275.5  870.01   276.2     870
   285.3  869.86   291.2  870.74     295  871.31   314.4  876.37   324.1  880.06
   333.8  885.38   401.6  924.79   411.3  930.31     421   935.4   430.7     940
#Mann= 3 , 0 , 0
       0     .06       0   276.2    .045       0   291.2      .1       0
Bank Sta=276.2,291.2
XS Rating Curve= 0 ,0
Exp/Cntr=0.3,0.1

Type RM Length L Ch R = 1 ,1268.6  ,91.7,83,74.1
XS GIS Cut Line= 4
     1602886.724      239544.379     1602656.213      239550.566
     1602563.982      239509.333     1602451.135      239490.887
#Sta/Elev= 30
       0     950    19.2  940.74    28.8  936.74      48  930.17    67.3  922.96
    86.5  915.34   105.7  907.12   124.9  897.93   134.5   892.3   144.1  885.21
   153.7  878.86   163.3  875.89     173  875.33   182.6  875.29     221  876.28
   230.6  876.42   239.8  876.16   258.2  874.86   267.3  873.49   276.5  871.35
   284.6  869.01   285.7  868.69   294.9  867.42   304.1  868.18   313.2  870.62
   331.6  876.94   341.2  880.43   350.7  884.64   388.8  903.23     446   930.5
#Mann= 3 , 0 , 0
       0     .06       0   284.6    .045       0   304.1      .1       0
Bank Sta=284.6,304.1
XS Rating Curve= 0 ,0
Exp/Cntr=0.3,0.1

Type RM Length L Ch R = 1 ,1185.6  ,177.1,177.4,177.7
XS GIS Cut Line= 2
     1602845.726      239454.551     1602482.341      239441.225
#Sta/Elev= 23
       0  920.01    39.3  903.06    49.1  898.59      59   893.7    68.8  888.56
    78.6  884.02    88.4  880.45    98.3  877.65   108.1  875.79   117.9  874.71
   137.6   873.2   196.6  869.11   216.2  867.56     226  866.93   235.9  867.31
   240.3  868.45   245.7  869.85   255.5  873.84   275.2  881.58     285  885.74
   314.5  898.72     344  911.43   363.6     920
#Mann= 3 , 0 , 0
       0     .06       0   216.2    .045       0   240.3      .1       0
Bank Sta=216.2,240.3
XS Rating Curve= 0 ,0
Exp/Cntr=0.3,0.1

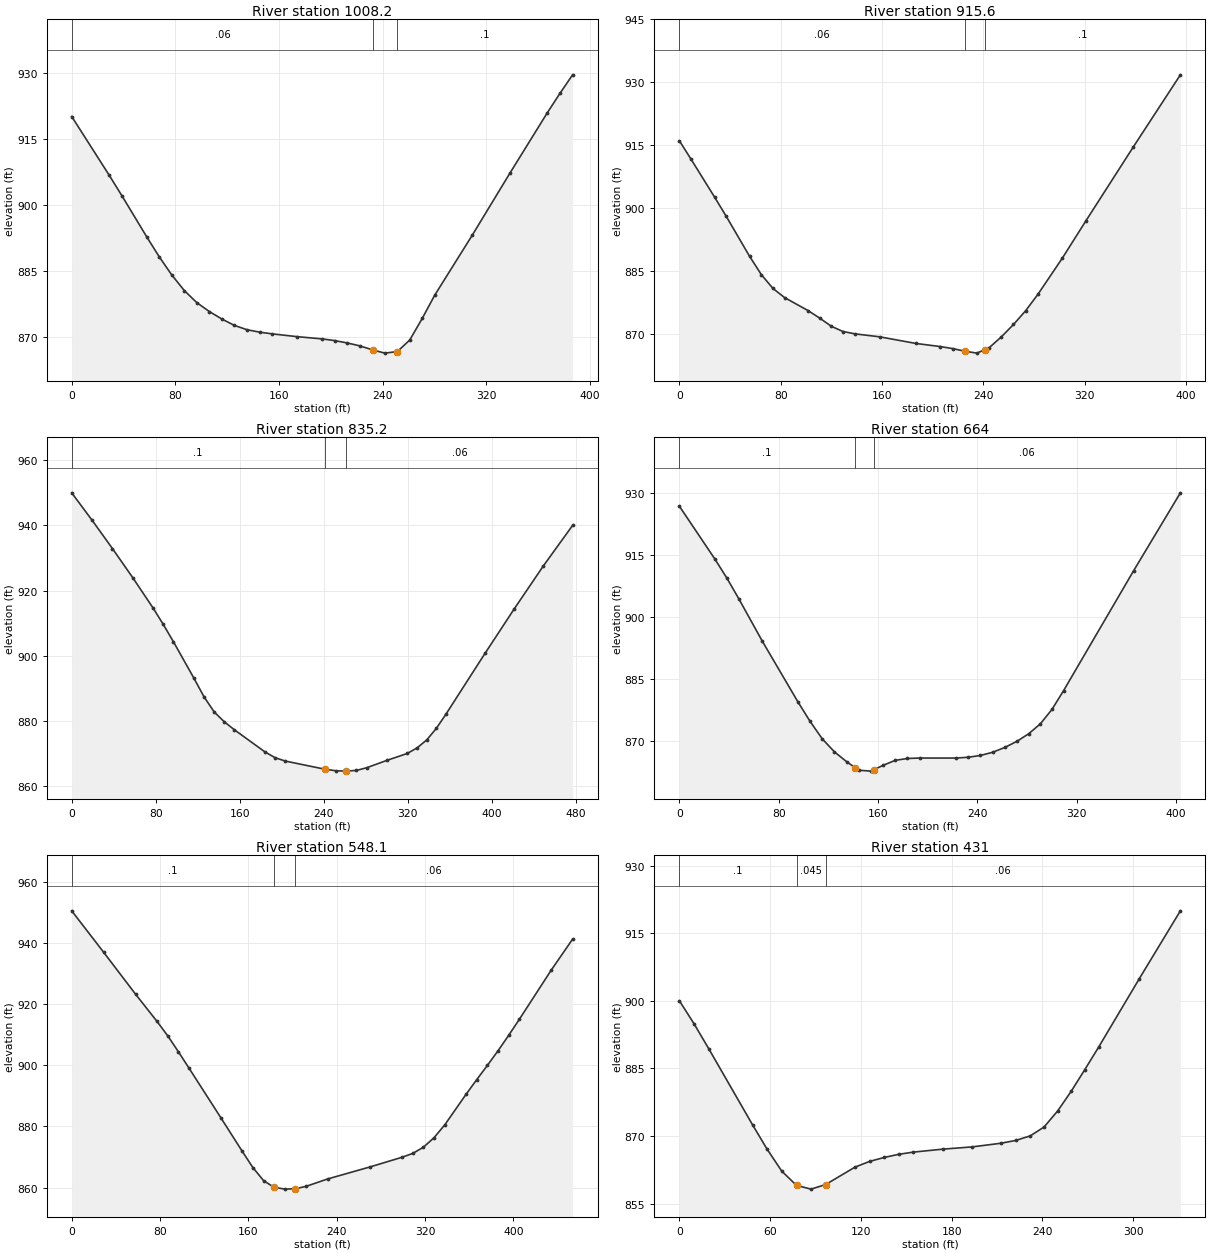
Type RM Length L Ch R = 1 ,1008.2  ,84.4,92.6,100.6
XS GIS Cut Line= 2
     1602864.404       239279.56     1602478.047      239267.214
#Sta/Elev= 30
       0  920.18      29  906.78    38.7  902.16      58  892.73    67.6  888.22
    77.3  884.07      87  880.52    96.6  877.79   106.3  875.76     116  874.05
   125.6  872.61   135.3  871.63     145  871.08   154.6  870.69     174  870.05
   193.3  869.54   202.9  869.16   212.6  868.62   222.3  867.96   232.5  867.02
   241.6   866.3   251.3  866.65   260.9  869.28   270.6  874.23   280.2   879.5
   309.2  893.17   338.2  907.27   367.2  921.08   376.9  925.47   386.6  929.67
#Mann= 3 , 0 , 0
       0     .06       0   232.5    .045       0   251.3      .1       0
Bank Sta=232.5,251.3
XS Rating Curve= 0 ,0
Exp/Cntr=0.3,0.1

Type RM Length L Ch R = 1 ,915.6   ,86.3,80.4,75.1
XS GIS Cut Line= 4
     1602862.376       239226.13     1602733.253      239225.045
     1602573.747      239157.771     1602480.431      239156.686
#Sta/Elev= 29
       0  916.07     9.2  911.68    27.7   902.7    36.9  898.12    55.3  888.62
    64.6  884.25    73.8  880.94      83  878.76   101.5  875.67   110.7  873.88
   119.9  871.93   129.1  870.68   138.8  870.11     158  869.42   186.8  867.83
   206.1  867.09   215.7  866.61   225.3     866   234.9  865.53   241.4  866.39
   244.5   866.8   254.2   869.4   263.8  872.35   273.4  875.63     283   879.5
   302.2  888.08   320.9     897   358.2  914.54   395.6  931.82
#Mann= 3 , 0 , 0
       0     .06       0   225.3    .045       0   241.4      .1       0
Bank Sta=225.3,241.4
XS Rating Curve= 0 ,0
Exp/Cntr=0.3,0.1

Type RM Length L Ch R = 1 ,835.2   ,182.5,171.2,159.1
XS GIS Cut Line= 4
     1602937.634      239155.796     1602763.635      239143.665
     1602622.256      239110.038     1602464.803      239112.998
#Sta/Elev= 30
       0     950    19.4  941.59    38.8   932.9    58.1  923.98    77.5  914.66
    87.2  909.63    96.9   904.3   116.3  893.18     126  887.43   135.7  882.76
   145.4  879.71     155  877.27   184.1  870.48   193.8   868.7   203.5  867.67
   240.9  865.19   251.9  864.68   261.6  864.58   271.3   864.8     281  865.62
   300.4  867.89   319.7     870     329   871.7   338.3  874.17   347.5  877.75
   356.8  882.19   393.8  900.74   421.6  914.38   449.4  927.59   477.2     940
#Mann= 3 , 0 , 0
       0      .1       0   240.9    .045       0   261.6     .06       0
Bank Sta=240.9,261.6
XS Rating Curve= 0 ,0
Exp/Cntr=0.3,0.1

Type RM Length L Ch R = 1 ,664     ,107.6,115.8,122.9
XS GIS Cut Line= 4
     1602884.077      238979.819     1602788.591      238980.905
     1602621.494      239037.687     1602489.766      239039.537
#Sta/Elev= 30
       0  926.73    28.6  913.97    38.2  909.41    47.8  904.42    66.8  894.15
    95.5   879.5   105.3  874.79   115.1  870.58   124.9  867.45   134.7  865.08
   141.4  863.67   144.5  863.02   154.3   862.8   156.4   863.1   164.1   864.2
   173.9  865.41   183.7  865.85   193.5  865.96     223  865.96   232.8  866.15
   242.6  866.59   252.4  867.35   262.2  868.52     272     870   281.4  871.82
   290.8   874.2   300.2   877.7   309.6  882.25   366.1  911.23   403.7     930
#Mann= 3 , 0 , 0
       0      .1       0   141.4    .045       0   156.4     .06       0
Bank Sta=141.4,156.4
XS Rating Curve= 0 ,0
Exp/Cntr=0.3,0.1

Type RM Length L Ch R = 1 ,548.1   ,116.3,117.1,117.7
XS GIS Cut Line= 2
     1602925.705      238882.225     1602472.792      238909.361
#Sta/Elev= 30
       0  950.65      29  937.04    57.9  923.31    77.2  914.46    86.9  909.74
    96.5  904.56   106.2  899.14   135.2   882.8   154.5  871.84   164.1  866.54
   173.8  862.25   183.2  860.09   193.1  859.47   202.7   859.6   212.4  860.39
   231.7  862.79   270.3  866.75   299.3  869.92   308.9  871.17   318.6  873.21
   328.2  876.32   337.9  880.52   357.2  890.53   366.8  895.31   376.5     900
   386.2  904.81   395.8  909.85   405.5  915.12   434.4  931.25   453.7  941.37
#Mann= 3 , 0 , 0
       0      .1       0   183.2    .045       0   202.7     .06       0
Bank Sta=183.2,202.7
XS Rating Curve= 0 ,0
Exp/Cntr=0.3,0.1

Type RM Length L Ch R = 1 ,431     ,137.2,130.4,123.9
XS GIS Cut Line= 3
     1602816.543      238781.785     1602584.646      238789.933
     1602494.271      238830.997
#Sta/Elev= 26
       0     900     9.7  894.88    19.3  889.41    48.3   872.5      58  867.05
    67.7  862.18    77.4  859.04      87  858.21    96.7  859.23     116  863.08
   125.7  864.36   135.4  865.24     145  865.94   154.7  866.43     174  867.08
   193.4  867.58   212.7   868.4   222.4  869.02     232  870.03   241.1  871.99
   250.1  875.55   259.1  879.94   268.1  884.75   277.2  889.72   304.2  904.97
   331.3     920
#Mann= 3 , 0 , 0
       0      .1       0    77.4    .045       0    96.7     .06       0
Bank Sta=77.4,96.7
XS Rating Curve= 0 ,0
Exp/Cntr=0.3,0.1

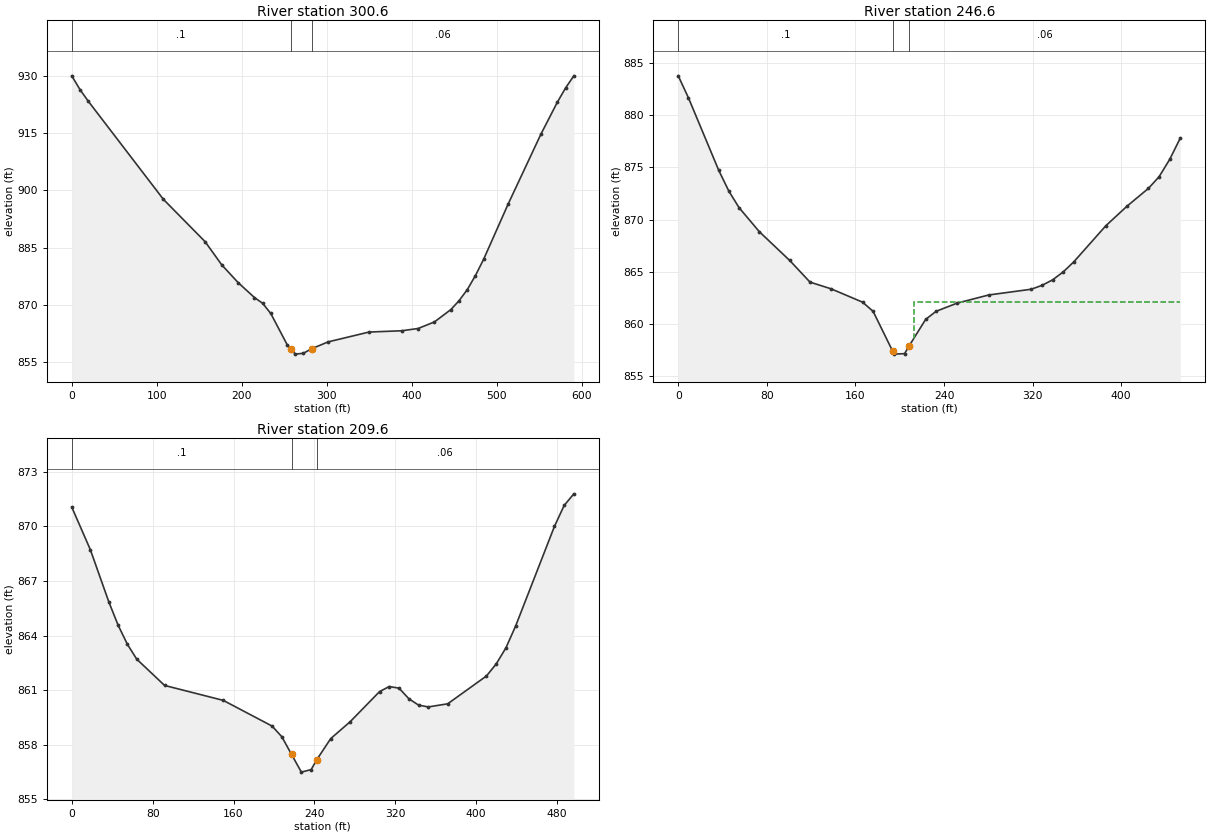
Type RM Length L Ch R = 1 ,300.6   ,54.7,54.1,53.2
XS GIS Cut Line= 4
     1602950.509      238730.387     1602808.122      238626.087
     1602625.831      238687.936     1602430.562      238793.328
#Sta/Elev= 30
       0     930     9.8  926.35    19.6   923.3   107.9  897.64   156.9  886.58
   176.5   880.5   195.8  875.85     215  871.94   224.6  870.44   234.2  867.77
   253.5  859.59   257.6  858.54   263.1  857.12   272.6  857.35   282.4  858.54
   301.6  860.32   349.8   862.9   388.3  863.24   407.6  863.83   426.9  865.56
   446.2   868.8   455.8  871.11   465.5  874.02   475.1   877.7   484.8     882
   513.7  896.48   552.3   914.8   571.6  923.14   581.2  926.84   590.9     930
#Mann= 3 , 0 , 0
       0      .1       0   257.6    .045       0   282.4     .06       0
Bank Sta=257.6,282.4
XS Rating Curve= 0 ,0
Exp/Cntr=0.3,0.1

Type RM Length L Ch R = 1 ,246.6   ,36.3,37,37.8
XS GIS Cut Line= 4
     1602906.864      238585.939     1602788.591      238572.918
     1602637.767      238630.427     1602475.006      238689.021
#Sta/Elev= 30
       0  883.77     9.2  881.67    36.6  874.72    45.8  872.72    54.9  871.16
    73.2  868.86   100.7   866.1     119  864.03     138  863.39   166.5  862.11
     176  861.23   193.6  857.43     195  857.14   204.4  857.19   208.6  857.94
   223.4  860.46   232.9  861.24   251.9  862.02   280.4   862.8   318.8  863.35
   328.5  863.72   338.1  864.25   347.7  865.01   357.3  865.98   386.1  869.42
   405.3   871.3   424.6     873   434.2  874.11   443.8  875.77   453.4  877.82
#Mann= 3 , 0 , 0
       0      .1       0   193.6    .045       0   208.6     .06       0
#XS Ineff= 2 , 0
                          212.68          862.11
Permanent Ineff=
       F       F
Bank Sta=193.6,208.6
XS Rating Curve= 0 ,0
Exp/Cntr=0.3,0.1

Type RM Length L Ch R = 1 ,209.6   ,199.4,209.6,219.7
XS GIS Cut Line= 4
     1602924.225      238543.622     1602835.249      238520.835
     1602597.619      238602.215      1602454.39      238657.554
#Sta/Elev= 30
       0  871.05    18.4  868.71    36.7  865.84    45.9  864.56    55.1  863.51
    64.3   862.7    91.8  861.26   149.8  860.44   198.1  859.03   207.8  858.44
   217.4  857.47   227.1   856.5   236.8  856.64   242.3  857.18   256.1  858.34
   275.4  859.27   304.4  860.92     314   861.2   323.7  861.11   333.4  860.53
     343  860.18   352.6  860.08   371.8  860.25   410.2  861.78   419.8  862.44
   429.4  863.32     439  864.52   477.4  869.99     487  871.14   496.6  871.78
#Mann= 3 , 0 , 0
       0      .1       0   217.4    .045       0   242.3     .06       0
Bank Sta=217.4,242.3
XS Rating Curve= 0 ,0
Exp/Cntr=0.3,0.1

Chan Stop Cuts=-1
Use User Specified Reach Order=0
Composite Channel Slope=5